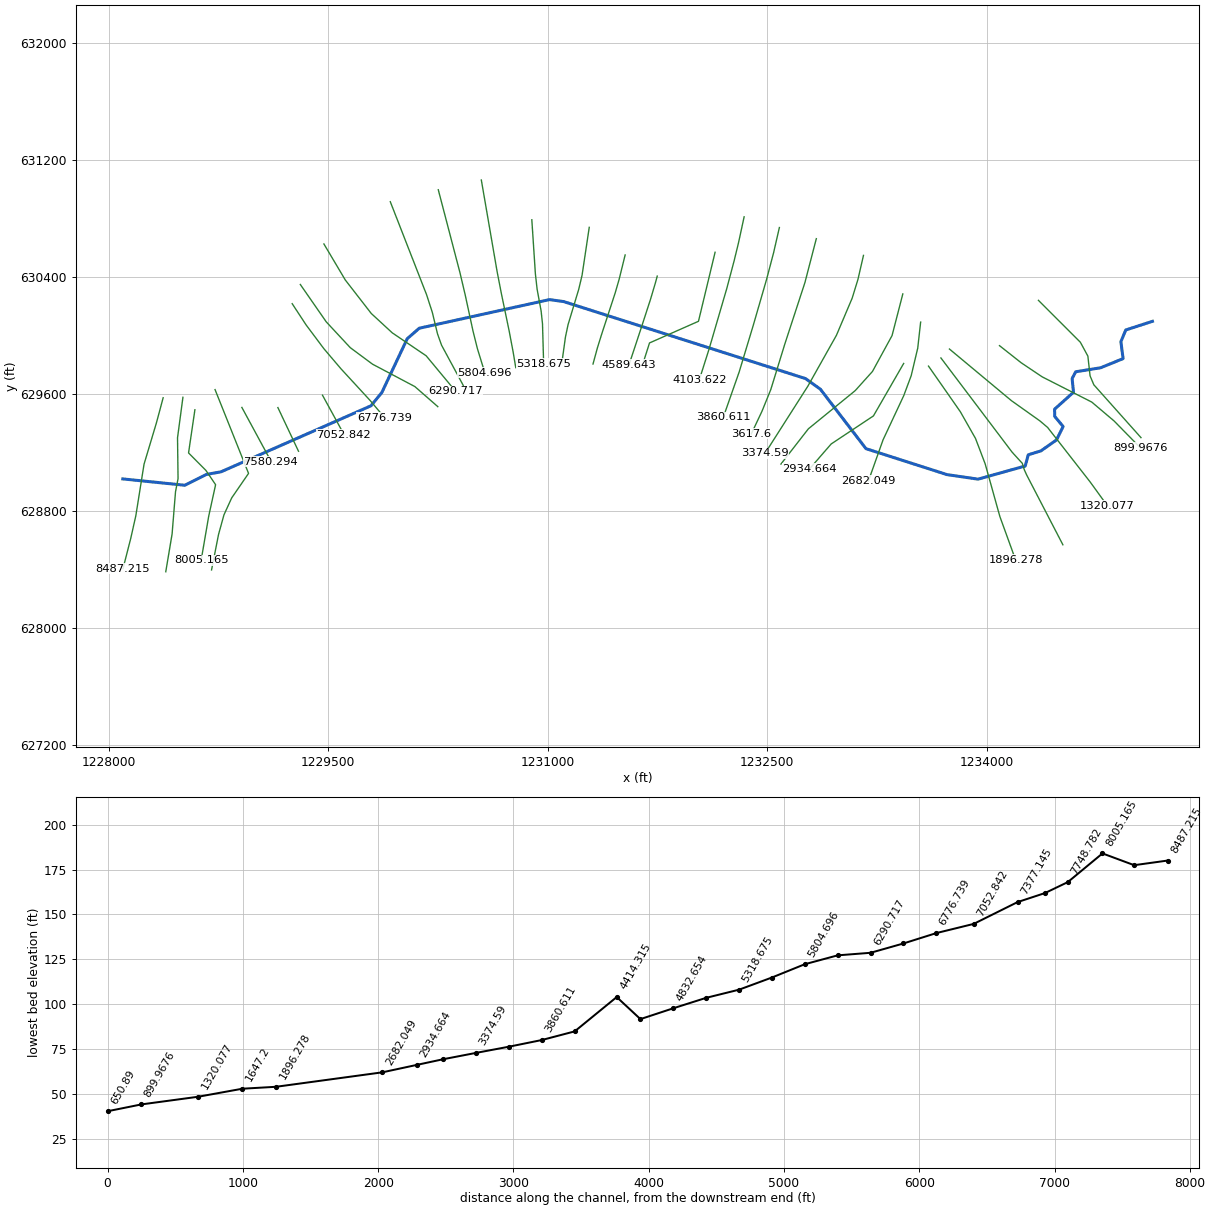
--- 677_ras.prj (project) ---

Proj Title=677
Current Plan=p01
Default Exp/Contr=0.3,0.1
English Units
Geom File=g01
Flow File=f01
Plan File=p01
Y Axis Title=Elevation
X Axis Title(PF)=Main Channel Distance
X Axis Title(XS)=Station
BEGIN DESCRIPTION:
RFD model 677 exported to HEC-RAS
END DESCRIPTION:

--- 677_ras.p01 (plan) ---

Plan Title=Plan 01
Program Version=4.10
Short Identifier=Plan 01
Geom File=g01
Flow File=f01
Subcritical Flow
Calc Critical at every XS
Secant Critical Depth

--- 677_ras.f01 (steady flow) ---

Flow Title=Flow 01
Program Version=5.01
Number of Profiles= 5
Profile Names=10yr,25yr,50yr,100yr,500yr
River Rch & RM=677,30,8487.215
    3300    4713    5880    7400   11000
Boundary for River Rch & Prof#=677,30,1
Up Type= 0
Dn Type= 2
Boundary for River Rch & Prof#=677,30,2
Up Type= 0
Dn Type= 2
Boundary for River Rch & Prof#=677,30,2
Up Type= 0
Dn Type= 2
Boundary for River Rch & Prof#=677,30,2
Up Type= 0
Dn Type= 2
Boundary for River Rch & Prof#=677,30,2
Up Type= 0
Dn Type= 2

--- 677_ras.g01 (geometry) ---

Geom Title=677
Program Version=4.10

River Reach=677,30
Reach XY= 30
1228094.70064783629021.5802253781228518.86718807628978.246892571
 1228666.3671467629052.4135329571228765.53378463629069.913524896
 1229791.2109271629521.4971083251229865.90923941629612.629043758
1230039.20932847629980.1447215081230121.37747115630051.855096281
1231011.78132784630247.5646413421231108.88913003630234.118942827
1232762.37318021629707.6780032371232864.03981477629635.178021818
1233175.70637766629228.5114668461233729.87287569629051.011503413
 1233942.1989226 629019.913389371234264.69883004629109.913353324
1234285.53215951629186.5799966161234372.19880131629213.246652871
1234478.86543876 629288.246627511234523.86542815629379.913265631
1234466.36544713629449.0799134221234465.53211546629498.246565536
 1234594.6987474629614.0798607321234585.53208613629707.413166597
1234609.69874704 629754.079818741234780.53203079629781.579805598
1234933.86532071 629844.079782591234918.86532849629959.913081959
1234952.19865435630039.913057238 1235134.6986022630099.079701081

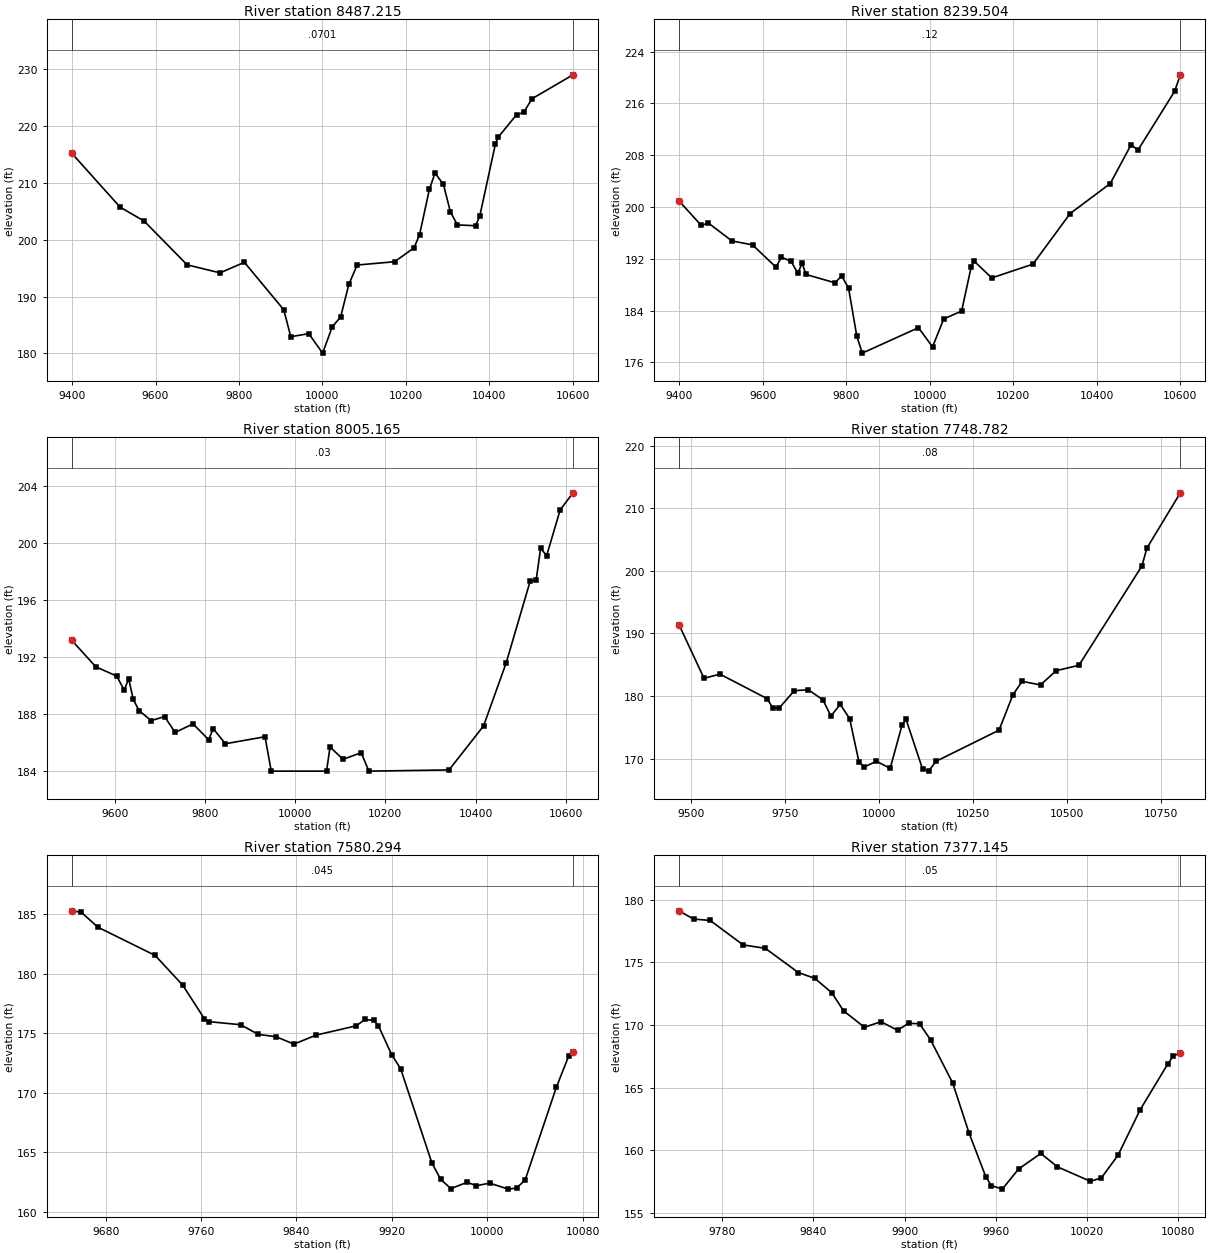
Type RM Length L Ch R = 1 ,8487.215,247.711500,247.711500,247.711500
XS GIS Cut Line= 6
 1228370.4987502629576.6083932531228325.01858282629406.792642885
1228239.78350049629122.3498682941228183.74171614  628770.5150749
1228148.75066398628614.1028361241228095.86617595628408.296666693
#Sta/Elev= 30
 9399.06215.24619515.019 205.7499572.759203.2815 9675.78195.57949754.781194.1637
9812.976196.03159907.523187.65459924.226 182.9149967.373183.454910000.57 180.024
10023.87184.683610043.73 186.38710063.58 192.16410083.44195.545910173.05196.1256
10219.68198.557710233.05200.890710256.58208.875710270.03211.7527 10290.2 209.757
10307.01204.905810323.82202.613610367.53202.468110377.61204.248810414.79216.8309
10421.57218.0668 10465.6222.027810482.54222.423410502.86224.855310600.97229.0565
#Mann= 3 , 0 , 0
 9399.06  0.0701       0 9399.06  0.0701       010600.97  0.0701       0
#XS Ineff= 2 , 0
       0 9834.11                       0
Bank Sta=9399.06,10600.97
Exp/Cntr=0.3,0.1

Type RM Length L Ch R = 1 ,8239.504,234.338700,234.338700,234.338700
XS GIS Cut Line= 6
1228505.67173824629579.5822333151228468.73123946 629302.78052359
1228472.35776878629022.9780123681228454.95728882628933.507819231
1228431.50646704628644.6022325691228388.39409087 628386.98172135
#Sta/Elev= 30
9399.099200.93419452.439197.15789469.059197.54399525.564194.77559575.241194.1551
9631.364190.7221 9644.53192.2489 9667.57191.62529684.012189.75029693.858191.3457
9703.704189.58329772.637188.30369789.056189.35899805.476187.4706 9825.18180.0724
9838.316177.44069973.083181.3706 10006.8178.402210033.63 182.72110076.51183.9323
10099.52190.7683 10106.1191.671910148.85189.054210247.53191.182210336.62198.9927
10432.76203.619910482.72209.604910499.39208.799410587.14217.863510600.94220.4173
#Mann= 3 , 0 , 0
9399.099    0.12       09399.099    0.12       010600.94    0.12       0
#XS Ineff= 2 , 0
       09865.549        10107.79       0
Bank Sta=9399.099,10600.94
Exp/Cntr=0.3,0.1

Type RM Length L Ch R = 1 ,8005.165,256.383600,256.383600,256.383600
XS GIS Cut Line= 6
1228587.55991623 629494.37537691 1228544.1571385629199.236488014
 1228663.0807496629079.4448213581228729.05297178628982.222599149
1228681.97985244628766.9415331331228630.26228938 628465.41943194
#Sta/Elev= 30
9505.005193.16879558.317191.31049604.742190.65969621.323189.67099631.271190.4844
 9641.22189.02499654.484188.23539681.013187.54069710.858 187.8219734.071186.7109
9773.864187.31069808.487186.19959818.554186.97779845.471185.91749933.308186.4098
9947.177     18410069.67     18410077.43185.685910106.31184.829710146.61185.2921
 10163.4     18410341.11184.083210417.68187.168510467.61191.567610520.87197.3037
10534.18197.385210544.17199.616210557.48199.100610587.44202.3061 10615.9203.5015
#Mann= 3 , 0 , 0
9505.005    0.03       09505.005    0.03       0 10615.9    0.03       0
#XS Ineff= 2 , 0
       09900.347        10089.39       0
Bank Sta=9505.005,10615.9
Exp/Cntr=0.3,0.1

Type RM Length L Ch R = 1 ,7748.782,168.487100,168.487100,168.487100
XS GIS Cut Line= 6
1228725.35886598629632.1793491691228954.36915222629059.350987256
1228838.89669782628891.3405155241228786.18528819628775.736347392
1228749.05765471628641.3038523051228701.41353676628399.347875834
#Sta/Elev= 30
9467.709191.36989534.208182.83579576.447 183.5089702.433179.58289716.562178.1582
9734.223178.08919774.721180.86199811.933181.00129850.788 179.4089872.102176.8092
9896.953178.68079921.924176.40439946.894169.44979961.163168.68349993.267169.5848
10029.97168.4668 10061.4175.341110072.16176.286210116.07168.367910132.09168.0138
10152.11169.585210319.95174.556410356.71180.206210381.42182.355310430.46181.7796
10471.67184.047110532.65184.921610700.29200.771410713.64203.634810802.73212.4623
#Mann= 3 , 0 , 0
9467.709    0.08       09467.709    0.08       010802.73    0.08       0
#XS Ineff= 2 , 0
       0                10063.76       0
Bank Sta=9467.709,10802.73
Exp/Cntr=0.3,0.1

Type RM Length L Ch R = 1 ,7580.294,203.149400,203.149400,203.149400
XS GIS Cut Line= 3
1228908.70241562629510.4024190461229107.27012396629143.648946807
1229106.64365748629140.233548403
#Sta/Elev= 30
 9651.44185.3073 9659.42185.19059673.202183.94259721.437181.55719744.567179.0596
9762.782176.23199766.952 175.9929793.068175.73679807.991174.92379822.915174.7275
9837.838174.10479856.492 174.867 9890.07175.64269897.531176.17929904.993176.0922
9908.724175.64589919.916173.20499927.378172.03649953.494164.14569960.956162.7408
9969.507161.96579983.289   162.59990.802162.208110001.99162.425710017.74161.9221
10024.63162.011510031.84162.696410057.96170.4714 10068.5173.146110071.97173.4553
#Mann= 3 , 0 , 0
 9651.44   0.045       0 9651.44   0.045       010071.97   0.045       0
#XS Ineff= 2 , 0
       0                               0
Bank Sta=9651.44,10071.97
Exp/Cntr=0.3,0.1

Type RM Length L Ch R = 1 ,7377.145,324.303500,324.303500,324.303500
XS GIS Cut Line= 2
1229155.01317951629509.3173495981229295.84582913629210.960773751
#Sta/Elev= 30
 9751.58179.12569761.124 178.4669772.008 178.3589793.776 176.3989808.288176.1325
9830.056174.1931 9840.94173.7238 9852.13  172.579859.816171.13119873.591169.8177
9884.475 170.2639895.359169.57269902.615170.13559909.871170.09599917.127168.8065
9931.639165.36989942.523161.32889953.407157.88389957.035157.16329964.291156.8746
9975.175   158.59989.687159.724210000.57158.659710022.34157.498610029.59157.7844
10040.48159.583510054.99163.206610073.13166.861310076.76167.5099 10081.5167.7791
#Mann= 3 , 0 , 0
 9751.58    0.05       0 9751.58    0.05       0 10081.5    0.05       0
#XS Ineff= 2 , 0
       0                               0
Bank Sta=9751.58,10081.5
Exp/Cntr=0.3,0.1

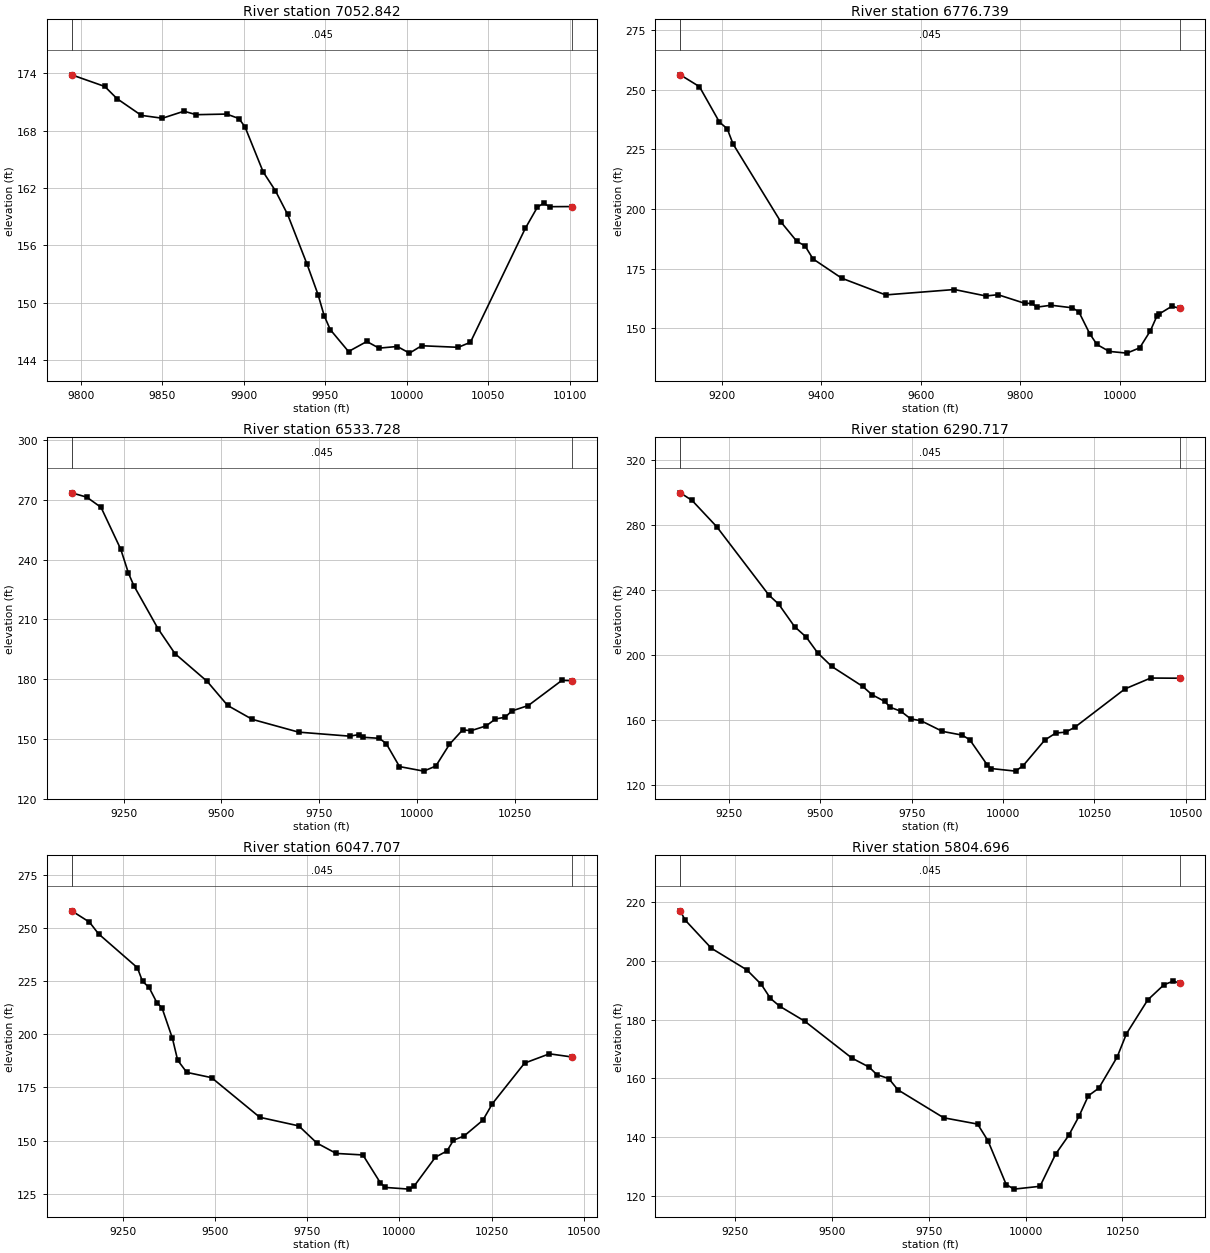
Type RM Length L Ch R = 1 ,7052.842,276.102700,276.102700,276.102700
XS GIS Cut Line= 3
1229459.91769338 629593.952766241229604.23192948629330.280891255
1229603.58308828 629323.94643411
#Sta/Elev= 30
9794.431173.85569814.731 172.6399822.211171.36859837.172169.61239850.105169.3125
9863.352170.04789870.833169.68499889.533169.74869897.013169.28469900.753168.4276
9911.974163.68739919.454161.72819926.934159.25219938.939154.01179945.635150.8529
9949.375148.66179953.115147.19419964.335144.89929975.555145.94979983.036145.2543
9994.256145.424910001.74144.731410009.22145.504510031.66145.339710039.14145.8654
 10072.8157.779410080.28160.016410084.02 160.41410087.76160.057410101.38160.0694
#Mann= 3 , 0 , 0
9794.431   0.045       09794.431   0.045       010101.38   0.045       0
#XS Ineff= 2 , 0
       0                               0
Bank Sta=9794.431,10101.38
Exp/Cntr=0.3,0.1

Type RM Length L Ch R = 1 ,6776.739,243.010600,243.010600,243.010600
XS GIS Cut Line= 6
1229252.63784274630219.8372524681229347.77760598630074.597972453
1229469.66734859629911.6541245431229585.71901065629775.180221573
1229785.48603493629558.0819845351229883.81438571629441.377052009
#Sta/Elev= 30
9117.205256.15299155.694251.20469195.893236.34449211.477 233.5819223.164227.2034
 9318.91194.64559351.311186.39429367.512184.56539383.712179.06669441.445170.9824
9529.502163.99489667.553166.25289730.718163.55159754.944164.08689808.242 160.501
9823.627160.41699832.544158.86549861.539159.67439903.879158.60539917.254156.9269
9939.063147.78339953.599143.2342 9978.22 140.34410013.75139.619810039.45141.8319
10060.86148.960810073.71155.0087   10078155.948210103.69 159.20710121.16 158.382
#Mann= 3 , 0 , 0
9117.205   0.045       09117.205   0.045       010121.16   0.045       0
#XS Ineff= 2 , 0
       0                               0
Bank Sta=9117.205,10121.16
Exp/Cntr=0.3,0.1

Type RM Length L Ch R = 1 ,6533.728,243.010700,243.010700,243.010700
XS GIS Cut Line= 6
1229308.25470593630351.0300497471229485.73975456 630095.30963077
1229649.88220446629919.0291877911229801.61990978629806.336813805
1230091.39723772629652.9789471111230248.40176924629515.671548307
#Sta/Elev= 30
9117.254273.47049155.951271.29279192.376266.17249242.754245.17319262.481233.1638
9276.022226.96659337.897205.36719381.343 192.8169463.749178.87099516.058166.7973
9579.057159.81749697.632153.4053 9828.08151.38639851.339152.14859862.833150.8189
9903.977150.30039921.702147.65919955.598136.119610017.61133.840910048.55136.3916
10083.43 147.27310116.91154.487710139.47154.182910177.45156.563810200.99160.0185
   10226160.891910242.69164.011910285.04166.753910370.95179.376810396.35179.2231
#Mann= 3 , 0 , 0
9117.254   0.045       09117.254   0.045       010396.35   0.045       0
#XS Ineff= 2 , 0
       0                               0
Bank Sta=9117.254,10396.35
Exp/Cntr=0.3,0.1

Type RM Length L Ch R = 1 ,6290.717,243.010700,243.010700,243.010700
XS GIS Cut Line= 6
1229469.60089083630628.1190286791229615.86435241630381.752691948
1229793.22195927630153.0256840181229937.02143622630020.274951543
1230168.69234292629863.4937230341230369.36821554629621.749816609
#Sta/Elev= 30
9117.277299.67899149.632294.9982 9217.17278.81149359.449236.89029386.617231.2229
9429.917217.44359461.801 211.0079492.935201.35789531.703192.95349616.381180.6921
9641.827175.58199676.525171.48869691.396167.86439720.548165.46689747.445160.7484
9775.403159.64079834.262153.07239888.365150.77159909.088147.89859956.036132.7078
9967.388130.246110034.15128.649410054.93131.998810114.22 147.76810144.33 152.076
10170.78152.584410196.18155.588310333.27179.160310403.64185.8527   10485185.7452
#Mann= 3 , 0 , 0
9117.277   0.045       09117.277   0.045       0   10485   0.045       0
#XS Ineff= 2 , 0
       0                               0
Bank Sta=9117.277,10485
Exp/Cntr=0.3,0.1

Type RM Length L Ch R = 1 ,6047.707,243.010600,243.010600,243.010600
XS GIS Cut Line= 6
1229923.41308277630917.1186993381230171.76695829630280.726845601
1230211.06447328 630159.458743081230246.34821887630013.302735506
1230273.98894174629936.0418958041230422.30608253629661.003499882
#Sta/Elev= 30
 9111.76258.01529159.953252.70829184.525247.20379289.831 231.2869303.872224.8356
9321.423222.04749342.518 214.9149356.654212.38859384.925198.05729399.061187.8089
9423.798182.09189490.943179.61779621.697160.98329727.388156.94469776.521 148.871
9828.754144.00559901.165143.29099948.725130.13679962.224128.026210026.34127.2299
10039.85128.593610097.78 142.25410129.11145.163210146.75150.230210175.43152.1957
10226.41159.618810252.29167.415710339.36186.441210406.72190.8161 10467.5189.3387
#Mann= 3 , 0 , 0
 9111.76   0.045       0 9111.76   0.045       0 10467.5   0.045       0
#XS Ineff= 2 , 0
       0                               0
Bank Sta=9111.76,10467.5
Exp/Cntr=0.3,0.1

Type RM Length L Ch R = 1 ,5804.696,243.010700,243.010700,243.010700
XS GIS Cut Line= 6
1230251.59347022630998.7364672791230399.96506473630431.301112553
1230435.30344419630281.3638244261230489.55040371630030.643412991
1230518.63283865629914.0149118991230569.55198197629748.352762271
#Sta/Elev= 30
 9109.03217.04519121.268213.95299189.134204.31789280.752196.94939318.078192.0073
9341.831187.21189365.584184.56859430.056179.47519552.165166.8826 9596.18163.8524
9616.495  161.269646.967159.93759670.668156.09839788.754146.58139876.276144.4371
9903.125138.7384 9950.11123.84719970.246122.285710037.38123.249610077.68134.2141
10111.29140.550810138.34147.194310162.01154.066210189.06156.669510236.53167.3025
10260.51175.213310315.31186.7019 10357.1191.861410380.56193.083910399.64 192.416
#Mann= 3 , 0 , 0
 9109.03   0.045       0 9109.03   0.045       010399.64   0.045       0
#XS Ineff= 2 , 0
       0                               0
Bank Sta=9109.03,10399.64
Exp/Cntr=0.3,0.1

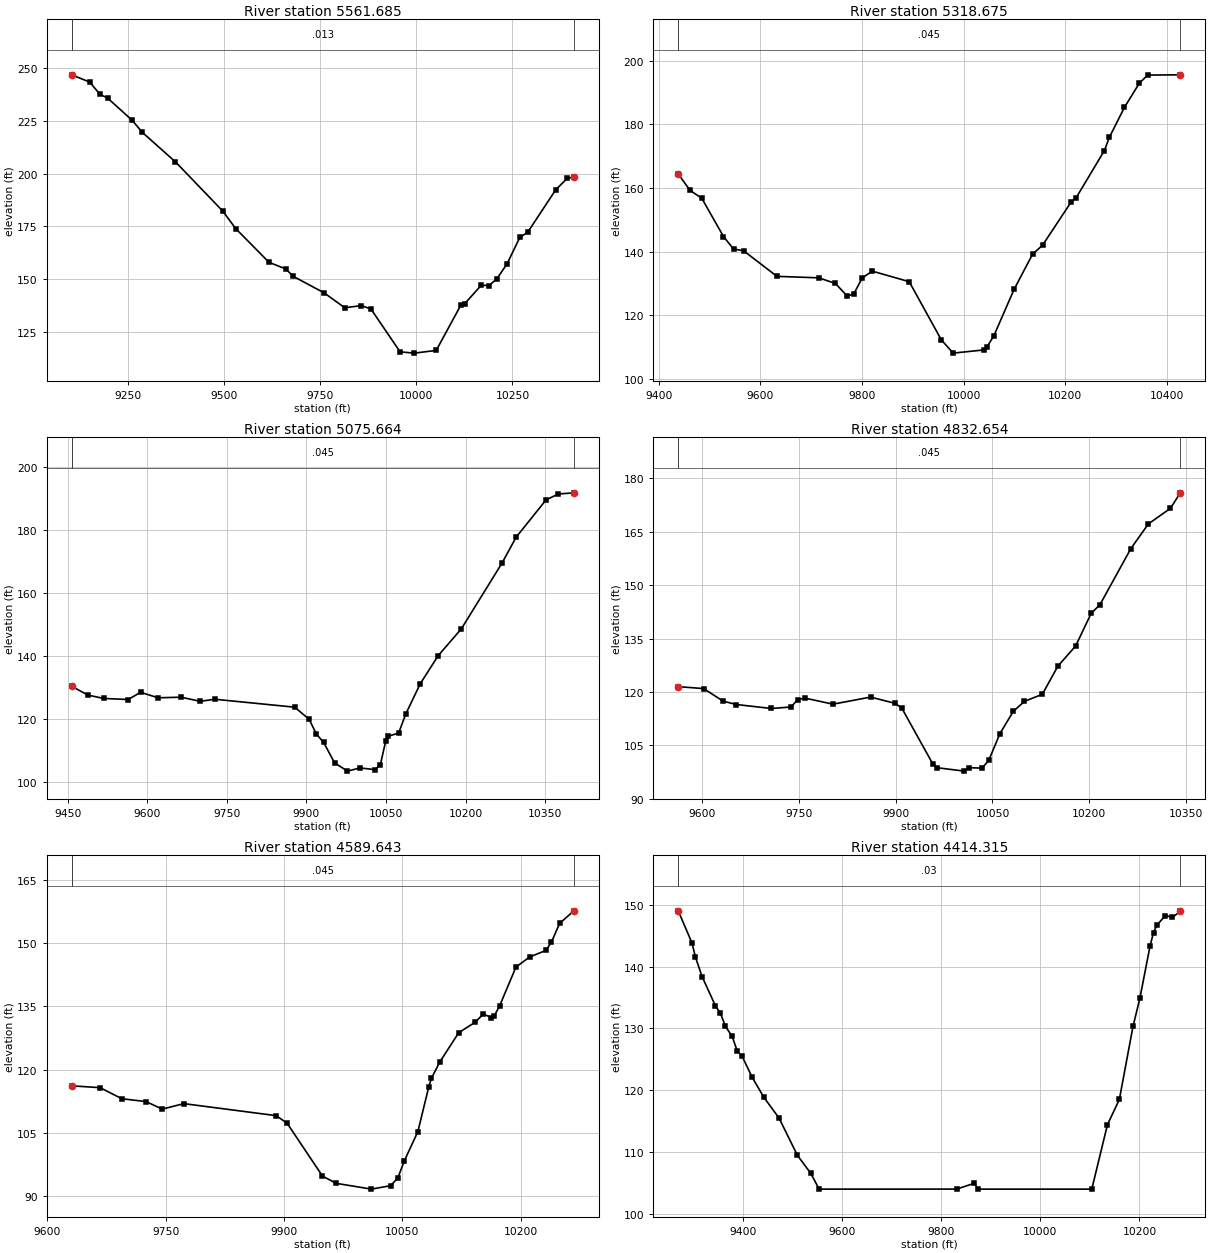
Type RM Length L Ch R = 1 ,5561.685,243.010700,243.010700,243.010700
XS GIS Cut Line= 6
1230545.89187141631065.5002774671230654.32935695   630436.657269
1230683.32101023630287.3275708941230736.27593942 630032.97037206
1230763.43050444629889.5133435351230781.42417521629782.490985684
#Sta/Elev= 30
9104.845 246.873 9151.31243.44069177.944237.66839197.919235.83729262.036225.2729
9287.809219.6388 9374.37205.57179497.552182.17559530.845173.94119617.405157.9329
9660.685154.83949680.661151.26389760.631143.46439814.104136.41959857.552137.4157
9882.233135.80719957.986115.4832 9994.85114.884710051.82116.164610115.49137.5622
10125.54138.277110169.06147.115510189.09146.923810209.13150.067110235.84 157.201
10269.23 169.83610289.27172.1393 10362.5192.392410392.44197.809210409.43 198.372
#Mann= 3 , 0 , 0
9104.845   0.013       09104.845   0.013       010409.43   0.013       0
#XS Ineff= 2 , 0
       0                               0
Bank Sta=9104.845,10409.43
Exp/Cntr=0.3,0.1

Type RM Length L Ch R = 1 ,5318.675,243.010600,243.010600,243.010600
XS GIS Cut Line= 6
1230891.24388331 630793.575530381230915.53376529630424.096824989
1230927.34753135630319.0633845031230954.72771886630169.799219891
1230964.24420178630081.7056055961230971.95098537629810.622461006
#Sta/Elev= 30
9438.523164.38019461.773159.22839484.782156.77059527.512144.73599547.234140.8161
9566.956140.27279632.695132.22039714.904131.75929747.802129.9963 9770.83126.0078
9783.989126.74149800.437  131.739820.217133.8592 9892.85130.54999955.973112.2883
9979.305108.106410039.37109.108510046.05110.1166 10059.4113.577110099.08128.1237
10135.38139.152810155.18142.0166   10211155.492510220.85156.830110276.67171.7025
10286.52175.887910316.05185.272710345.58192.935110361.99195.448810426.08195.5292
#Mann= 3 , 0 , 0
9438.523   0.045       09438.523   0.045       010426.08   0.045       0
#XS Ineff= 2 , 0
       0                               0
Bank Sta=9438.523,10426.08
Exp/Cntr=0.3,0.1

Type RM Length L Ch R = 1 ,5075.664,243.010700,243.010700,243.010700
XS GIS Cut Line= 6
1231283.75514072630741.5022914261231234.91209254 630415.14748928
1231212.17702848630318.8771104661231138.72451907630075.589625835
1231121.18376732629992.005865693 1231096.6509518629816.049494818
#Sta/Elev= 30
9457.667130.49469488.057127.71029517.781126.64659564.018126.3067 9587.24128.5912
9620.417126.85179663.546127.03669700.065125.73139726.776126.39239877.888123.8696
9905.098120.00969918.762 115.3299932.425112.66519952.951 106.2199977.112103.5693
   10001104.581910028.87 104.04410039.22105.550910049.57113.270910053.01114.6216
 10073.7115.626410087.29121.739510114.49131.312610148.38140.237810191.96148.7469
10268.65169.632110295.22177.834610351.56 189.66510374.68 191.54610403.99191.9192
#Mann= 3 , 0 , 0
9457.667   0.045       09457.667   0.045       010403.99   0.045       0
#XS Ineff= 2 , 0
       0                               0
Bank Sta=9457.667,10403.99
Exp/Cntr=0.3,0.1

Type RM Length L Ch R = 1 ,4832.654,243.010700,243.010700,243.010700
XS GIS Cut Line= 6
1231529.25433391630552.8162676241231488.10990062630386.001372218
1231461.07018143 630292.902104811231368.86342451630011.543341324
1231339.72786963629917.8366171571231309.61746413629807.321359068
#Sta/Elev= 30
9563.323121.48249602.625120.93659632.983117.39699653.312116.46299707.525115.3493
9738.043115.76529748.292117.80859759.234118.27319802.955116.55999861.304118.5518
9899.235116.7873 9909.58115.44239957.85699.677329964.753 98.702610006.1597.75283
10013.0798.7169910033.8298.5972210044.19100.766410061.48108.286710082.23114.5377
10099.52117.353510127.18119.328410151.24127.231110178.73132.905110202.78142.0512
10216.52144.533210264.26160.256410291.49167.207210325.53171.557110340.87175.9235
#Mann= 3 , 0 , 0
9563.323   0.045       09563.323   0.045       010340.87   0.045       0
#XS Ineff= 2 , 0
       0                               0
Bank Sta=9563.323,10340.87
Exp/Cntr=0.3,0.1

Type RM Length L Ch R = 1 ,4589.643,175.327700,175.327700,175.327700
XS GIS Cut Line= 6
1231748.67065033630408.1827897731231737.03912354630365.017732248
1231702.87985706630250.0969256461231640.04657078630056.716814235
   1231561.47527629819.5395900911231556.13327616629801.610508323
#Sta/Elev= 30
9631.073116.19289667.109115.75269694.428113.13969725.232112.46039745.768110.6741
 9773.15111.97439890.261109.1271 9904.06 107.3369948.906 94.80959966.15493.09242
10011.0391.7178810035.2292.5363710044.4494.35388 10052.598.3556410069.78105.3176
 10083.6 115.91910087.06 117.99510097.43121.778710121.62128.785810142.36131.2461
10152.73133.202810163.09132.373410166.55132.711110173.46135.1377 10194.2144.3352
10211.48146.720210232.22148.276910239.13150.241910249.49154.679110267.56157.6581
#Mann= 3 , 0 , 0
9631.073   0.045       09631.073   0.045       010267.56   0.045       0
#XS Ineff= 2 , 0
       0                               0
Bank Sta=9631.073,10267.56
Exp/Cntr=0.3,0.1

Type RM Length L Ch R = 1 ,4414.315,310.693600,310.693600,310.693600
XS GIS Cut Line= 5
1232144.17356575630571.0896737471232030.62689952630099.330310632
1231695.75814516629951.1952230081231687.70215816629925.314152558
  1231646.609612629796.917232593
#Sta/Elev= 30
9269.064149.01359296.936143.79029303.685141.55839317.183138.37459344.179133.6407
9354.303132.44279364.427130.32059377.925128.69319388.048 126.3649398.172125.4644
9418.419122.06549442.041118.83029472.411115.51259509.531 109.4699536.527106.5614
  9553.4     1049831.072104.00439866.966104.95389874.141     10410103.74     104
10135.29114.419310159.38118.506810186.93 130.33610200.71134.840610221.38143.3615
10228.27145.490210235.16146.708810252.39148.249610266.16147.959510282.38148.9093
#Mann= 3 , 0 , 0
9269.064    0.03       09269.064    0.03       010282.38    0.03       0
#XS Ineff= 2 , 0
       09856.256                       0
Bank Sta=9269.064,10282.38
Exp/Cntr=0.3,0.1

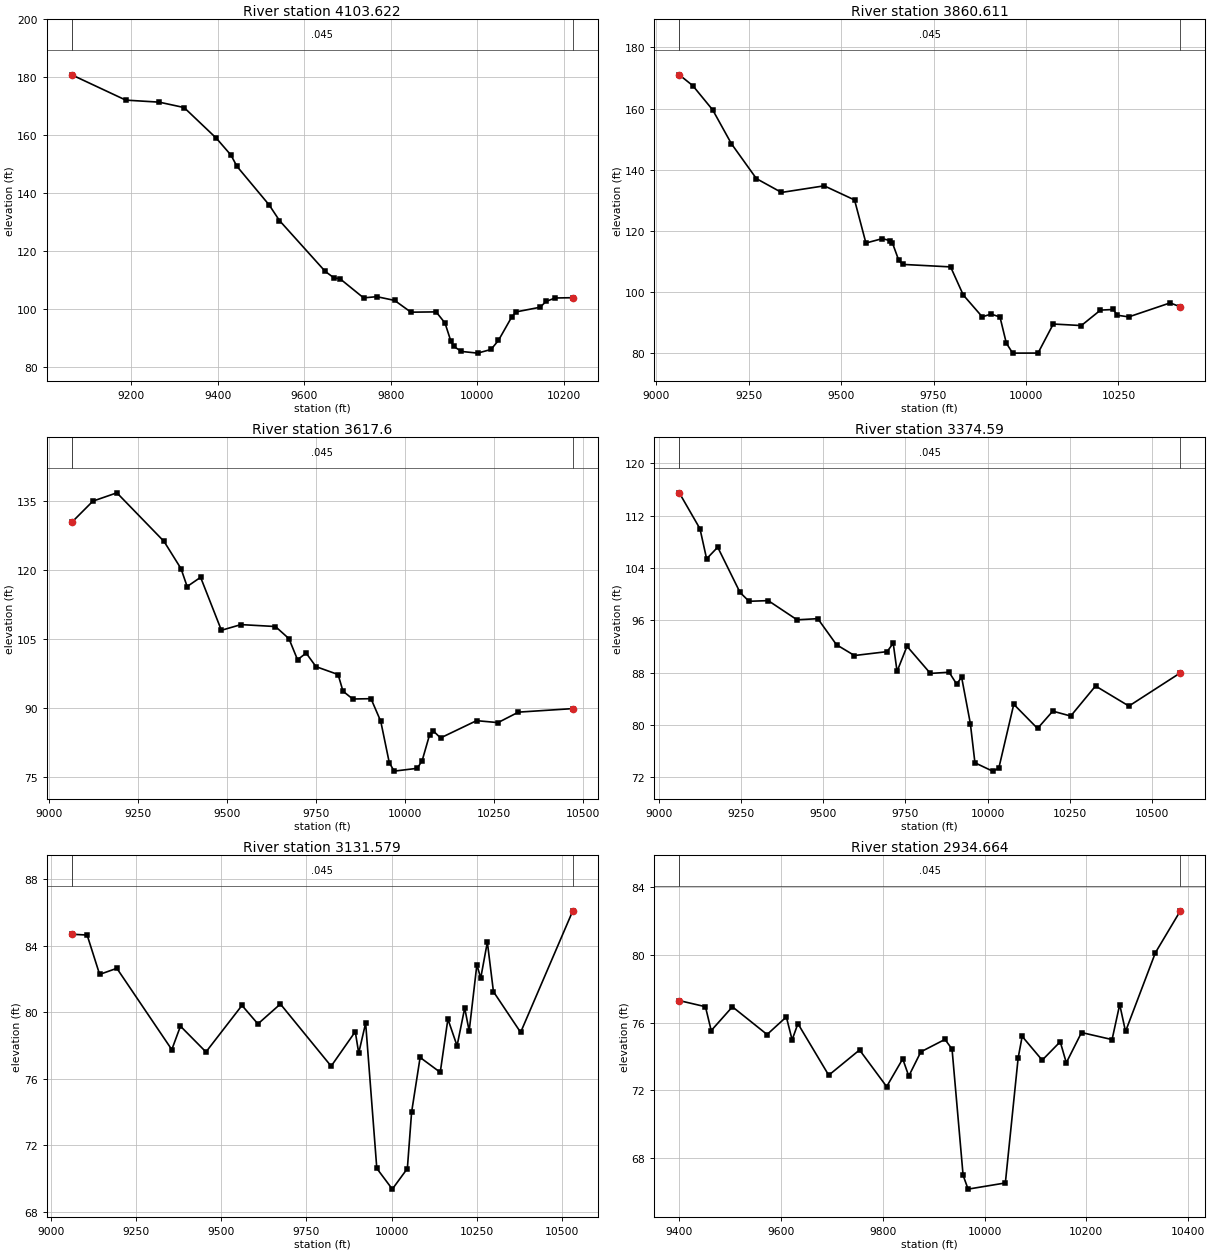
Type RM Length L Ch R = 1 ,4103.622,243.010700,243.010700,243.010700
XS GIS Cut Line= 6
 1232342.8594285630813.7212463321232304.52362296630636.527240342
1232274.29790423630512.2951055311232224.40567524630324.348249722
1232102.98464753629908.9502316551232035.83315985629697.929394362
#Sta/Elev= 30
9062.605180.84739187.523172.1257 9264.85171.42329322.252169.56479396.667159.0096
9430.612153.15529444.353149.29799518.868135.97249542.629 130.5979648.271113.0776
9668.741110.81299682.387 110.5479736.974103.93829767.679104.34579808.745103.0528
9846.41299.002169904.62499.10273 9925.1795.252489938.86788.926789945.71687.17811
9962.83785.4691210000.5184.8806210031.4386.1419710048.6189.2578410079.5397.39321
10089.8399.1067910144.89100.702710158.71102.703310179.43 103.89210220.45103.9988
#Mann= 3 , 0 , 0
9062.605   0.045       09062.605   0.045       010220.45   0.045       0
#XS Ineff= 2 , 0
       0                               0
Bank Sta=9062.605,10220.45
Exp/Cntr=0.3,0.1

Type RM Length L Ch R = 1 ,3860.611,243.010700,243.010700,243.010700
XS GIS Cut Line= 6
1232583.88041255630740.4196841191232544.19858925630567.643033442
1232496.63876644630387.0562067881232405.92811104  630073.9381659
1232308.98118653629753.0145006011232199.94270137629442.062097962
#Sta/Elev= 30
9062.608171.05499099.205167.50519153.065159.56369203.558148.52449271.127137.1214
9338.981132.60049454.521134.76189536.499130.1394 9567.24116.06049611.645117.5027
9632.338116.84519638.971116.07029656.049 110.3989666.297109.07599796.203108.2578
9830.44699.076869881.80991.925779905.77992.839269929.74991.86064 9946.8783.33235
9963.99280.0648710032.5980.0846110073.8289.58102 10149.789.0793910201.4994.13334
10236.2494.3291710246.6792.4571110277.9891.9146610389.8296.4885610417.4495.19304
#Mann= 3 , 0 , 0
9062.608   0.045       09062.608   0.045       010417.44   0.045       0
#XS Ineff= 2 , 0
       0                10090.62       0
Bank Sta=9062.608,10417.44
Exp/Cntr=0.3,0.1

Type RM Length L Ch R = 1 ,  3617.6,243.010600,243.010600,243.010600
XS GIS Cut Line= 6
1232836.43936129630664.350212705 1232758.2779896630363.512102745
 1232620.9724076629943.6093715381232525.07795436 629632.48201994
1232464.94028015629484.2602241711232391.95948501 629329.51802383
#Sta/Elev= 30
9062.611130.4145 9122.15135.02799189.626136.83259322.307126.26589370.068120.3482
9387.244116.46469425.099118.47489483.601 106.9599538.708108.19569635.521107.7777
9673.555105.14579697.758 100.5639721.962102.00639749.62399.06025 9811.8697.34368
9825.59693.726829853.00792.027319904.40292.094339931.81287.182489955.79678.18951
9969.50276.3523710034.5776.9632810048.2678.6307210068.9384.1925910079.29 85.1043
10100.03 83.565710201.26 87.320410261.58 86.8974   1031989.1714610471.9889.93881
#Mann= 3 , 0 , 0
9062.611   0.045       09062.611   0.045       010471.98   0.045       0
#XS Ineff= 2 , 0
       0                10080.58       0
Bank Sta=9062.611,10471.98
Exp/Cntr=0.3,0.1

Type RM Length L Ch R = 1 , 3374.59,243.010700,243.010700,243.010700
XS GIS Cut Line= 6
1233158.85968161630549.7764608421233120.67212143 630384.39015593
1233081.51011247630257.2503072121232973.87299567630003.389817576
1232777.89899415629654.6152622731232485.39152193629196.016202132
#Sta/Elev= 30
9062.638115.5042 9125.57109.99969145.694105.40519179.449107.18279247.283100.2565
9274.61898.902659333.01899.003379420.66196.065779483.59496.242839540.47592.25354
9595.06190.600349694.24691.197579712.82892.482399724.54688.167329754.74192.01768
9825.82687.862699882.77888.041669905.55986.234029920.74687.275359947.32480.17965
9961.22474.1815510014.8572.9057610033.6773.3375710079.25 83.137210151.52 79.4354
10197.7782.0891210252.3181.3368910327.7585.9384610429.1982.8655310585.5887.94824
#Mann= 3 , 0 , 0
9062.638   0.045       09062.638   0.045       010585.58   0.045       0
#XS Ineff= 2 , 0
       0                10088.82       0
Bank Sta=9062.638,10585.58
Exp/Cntr=0.3,0.1

Type RM Length L Ch R = 1 ,3131.579,196.914700,196.914700,196.914700
XS GIS Cut Line= 6
1233427.90173183630286.7018903831233354.13834346630001.382116171
1233220.31123782 629756.415434211233102.32539514629625.247119841
1232782.16744053629364.1919210151232594.48642441629123.141942283
#Sta/Elev= 30
9060.97584.694929106.24784.646379142.92482.280329193.47182.647239354.84777.75971
 9380.2879.169679455.20277.619329560.91780.417649607.70279.304629673.70980.50139
 9822.7676.765489893.59278.838669903.73377.552559924.06179.356479956.84170.62212
10002.36 69.375810046.56 70.611910058.9873.9947610084.01 77.290410143.1376.39482
10165.5879.5979310192.5177.9883610214.9680.2630710228.0878.8761110250.6782.86291
10261.9782.0586410281.43 84.221610299.33  81.24410379.1978.7987110532.3686.10201
#Mann= 3 , 0 , 0
9060.975   0.045       09060.975   0.045       010532.36   0.045       0
#XS Ineff= 2 , 0
       09896.709        10081.75       0
Bank Sta=9060.975,10532.36
Exp/Cntr=0.3,0.1

Type RM Length L Ch R = 1 ,2934.664,252.615400,252.615400,252.615400
XS GIS Cut Line= 4
1233433.62553638629810.9687118531233226.90831086629452.326778412
1232938.00230893629260.5529667881232791.05873898 629091.19427599
#Sta/Elev= 30
9399.864 77.29189451.26776.931529462.62775.523319504.28276.926819572.445 75.2939
9610.313 76.33179621.67374.977059633.03475.934059693.62272.896189754.21174.38368
9807.46772.223919839.08773.860769850.95272.842639874.68274.27247 9922.1475.00542
9936.02174.433319957.73467.005379967.52466.1857410040.79 66.549410065.9773.91736
10073.8575.1842310113.2273.7821910148.6774.8674310160.58 73.628210190.4975.40986
10250.56 74.995310265.5877.0601710277.0275.4730610335.6780.10829 10384.882.57936
#Mann= 3 , 0 , 0
9399.864   0.045       09399.864   0.045       0 10384.8   0.045       0
#XS Ineff= 2 , 0
       09870.328        10077.44       0
Bank Sta=9399.864,10384.8
Exp/Cntr=0.3,0.1

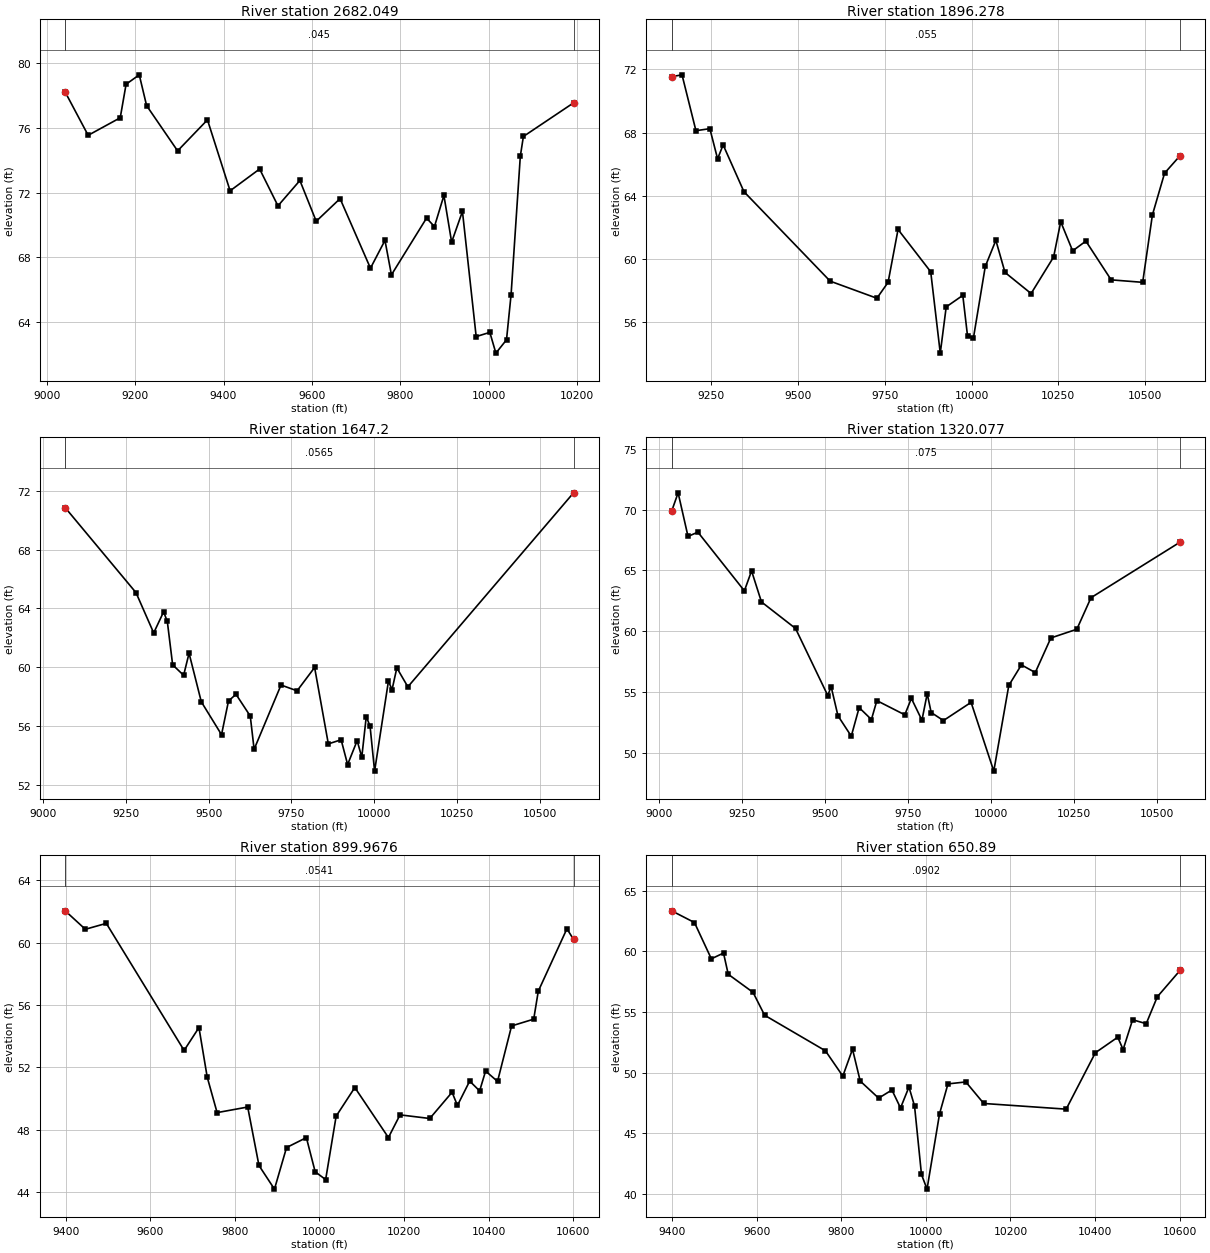
Type RM Length L Ch R = 1 ,2682.049,785.770800,785.770800,785.770800
XS GIS Cut Line= 6
 1233549.7240217630093.7663297831233529.74888338629915.355639966
1233485.07845694 629727.283845071233434.30836226629591.157404648
1233292.72654032629288.7485082871233192.83016299629007.830637862
#Sta/Elev= 30
9041.64478.221219093.59375.548279166.19576.632259179.44978.705799209.27179.28803
9225.87677.38366 9296.06 74.58659363.65376.504099414.907  72.1169481.72273.46478
9523.24271.185479572.87672.754179609.83170.231969663.83371.633039732.60167.33031
9765.454  69.0519780.05666.919519859.53670.42709 9877.4769.905969898.86471.82988
9916.34968.942019940.82770.841819971.89863.1020710002.79 63.363210016.52 62.0791
10040.5562.9020910050.9265.69852 10071.874.2496110078.7675.4757210192.2877.55392
#Mann= 3 , 0 , 0
9041.644   0.045       09041.644   0.045       010192.28   0.045       0
#XS Ineff= 2 , 0
       0  9884.5        10087.39       0
Bank Sta=9041.644,10192.28
Exp/Cntr=0.3,0.1

Type RM Length L Ch R = 1 ,1896.278,249.077500,249.077500,249.077500
XS GIS Cut Line= 6
1233603.43125302629792.9728463441233821.29770851629480.727735415
1233925.02857816629297.8630374671233990.94338262629124.406874746
1234091.32820371628764.5840848831234198.81279299 628468.28869696
#Sta/Elev= 30
9135.307 71.54419165.13271.660499205.26768.120199245.40268.251069267.68166.33766
9283.683 67.22319343.69164.258069592.32958.589689727.023  57.5079759.31458.51581
9788.01761.862829882.18859.184249909.75154.03013 9926.8656.958199974.71157.68924
9988.382 55.111210005.4755.0010110039.5459.5217910070.0461.17693 10096.459.14208
10171.65 57.804810236.55  60.11910257.0862.3527410291.4360.50937 10329.661.12677
10402.4658.6717910493.3758.5151410521.4362.7854710556.5165.4312110600.9866.53364
#Mann= 3 , 0 , 0
9135.307   0.055       09135.307   0.055       010600.98   0.055       0
#XS Ineff= 2 , 0
       09677.951        10070.41       0
Bank Sta=9135.307,10600.98
Exp/Cntr=0.3,0.1

Type RM Length L Ch R = 1 ,  1647.2,327.123400,327.123400,327.123400
XS GIS Cut Line= 6
1233688.27288198629848.6501653491234174.70645609 629204.96923548
1234244.80156565629128.0025472491234258.71075583629083.757749215
 1234274.8358236629048.1747155491234522.16965809628571.462016597
#Sta/Elev= 30
9067.30270.845669280.93165.073019334.27762.337889364.12563.767289375.31263.12692
9391.43660.171469424.55559.460159440.96960.959459477.90157.660139538.91455.42795
9559.97257.718419582.61158.169119625.62956.692879637.232 54.43359718.41858.80037
9766.86858.405489819.76859.99204 9861.15 54.8015 9899.7355.08135 9919.3853.39867
9948.12455.021479962.06653.898569975.57356.651039987.03656.0071610000.7452.95153
10042.5459.0726410053.3558.4793210067.8659.9643310101.1258.6771810600.9471.85376
#Mann= 3 , 0 , 0
9067.302  0.0565       09067.302  0.0565       010600.94  0.0565       0
#XS Ineff= 2 , 0
       09593.484        10062.69       0
Bank Sta=9067.302,10600.94
Exp/Cntr=0.3,0.1

Type RM Length L Ch R = 1 ,1320.077,420.109400,420.109400,420.109400
XS GIS Cut Line= 6
1233746.60150191629909.6300861541234170.27948225629556.757405654
 1234365.8775757629417.7025290281234417.73023874629373.677322537
1234707.99649447629001.842941508 1234826.3335939  628838.3147524
#Sta/Elev= 30
9037.61469.891519057.05771.395259086.88167.807539116.70568.156869256.92563.32523
9278.60564.965859308.42862.410629411.20160.227029508.43254.70375 9518.5655.43885
9539.15953.037159579.33451.355549603.09453.708029640.10552.727939656.55554.28285
9740.74653.115169760.64254.466659792.47452.670369808.39154.855629820.32853.30547
9857.31252.641569940.69154.1421310009.1848.4776710054.4555.5306610092.5257.22741
10134.3256.5951310181.34 59.444210259.7160.1625210302.4162.7594810570.8767.33099
#Mann= 3 , 0 , 0
9037.614   0.075       09037.614   0.075       010570.87   0.075       0
#XS Ineff= 2 , 0
       09527.691                       0
Bank Sta=9037.614,10570.87
Exp/Cntr=0.3,0.1

Type RM Length L Ch R = 1 ,899.9676,249.077600,249.077600,249.077600
XS GIS Cut Line= 6
1234088.82813989629932.7906901721234237.22319717629815.659435204
1234380.10641818 629719.767470711234719.78887746629546.921735586
1234871.97728946629418.1173788181235053.22706839 629233.38315696
#Sta/Elev= 30
9399.06262.028619446.67860.846549496.23461.225829680.18253.087129715.28754.55124
9734.79151.380639758.19449.104279830.537 49.46229857.17345.717749893.78844.20378
 9922.3746.86708 9969.2647.50259 9990.0545.3162810014.8244.8142510039.6648.87736
10083.8150.7104810163.2447.5070710190.6948.9603110261.0648.7279110313.7350.40794
10326.4249.5621310355.3851.1242910378.8950.49398   10393 51.766210421.2251.10381
10454.4754.6564610506.7755.0904610517.57 56.882510585.2460.8766310600.9260.20209
#Mann= 3 , 0 , 0
9399.062  0.0541       09399.062  0.0541       010600.92  0.0541       0
#XS Ineff= 2 , 0
       09625.455                       0
Bank Sta=9399.062,10600.92
Exp/Cntr=0.3,0.1

Type RM Length L Ch R = 1 ,  650.89,0.000000,0.000000,0.000000
XS GIS Cut Line= 6
1234354.97775955630242.6592742431234641.85595231629955.857011778
1234693.09586547629861.3076985581234708.24978674629725.968697525
 1234733.9958195 629664.972512631235056.23257671629303.961213289
#Sta/Elev= 30
9399.11363.337429452.94362.373499492.88359.382949521.66859.859489532.823  58.111
9591.49356.62013  9618.854.736989762.56551.808489803.71649.721939826.63151.93951
9844.82349.314389888.37947.908029919.80148.577649940.16347.097919960.08748.82404
9973.24547.263259989.66341.62057 10002.840.4111610032.3946.6173210052.2949.08009
10094.5449.2412610136.8647.4674410331.7246.9992810400.7751.6467410453.6652.92585
10466.3651.90751 10488.854.3655210520.9754.0400510547.1556.2524110600.8458.42592
#Mann= 3 , 0 , 0
9399.113  0.0902       09399.113  0.0902       010600.84  0.0902       0
#XS Ineff= 2 , 0
       0                               0
Bank Sta=9399.113,10600.84
Exp/Cntr=0.3,0.1